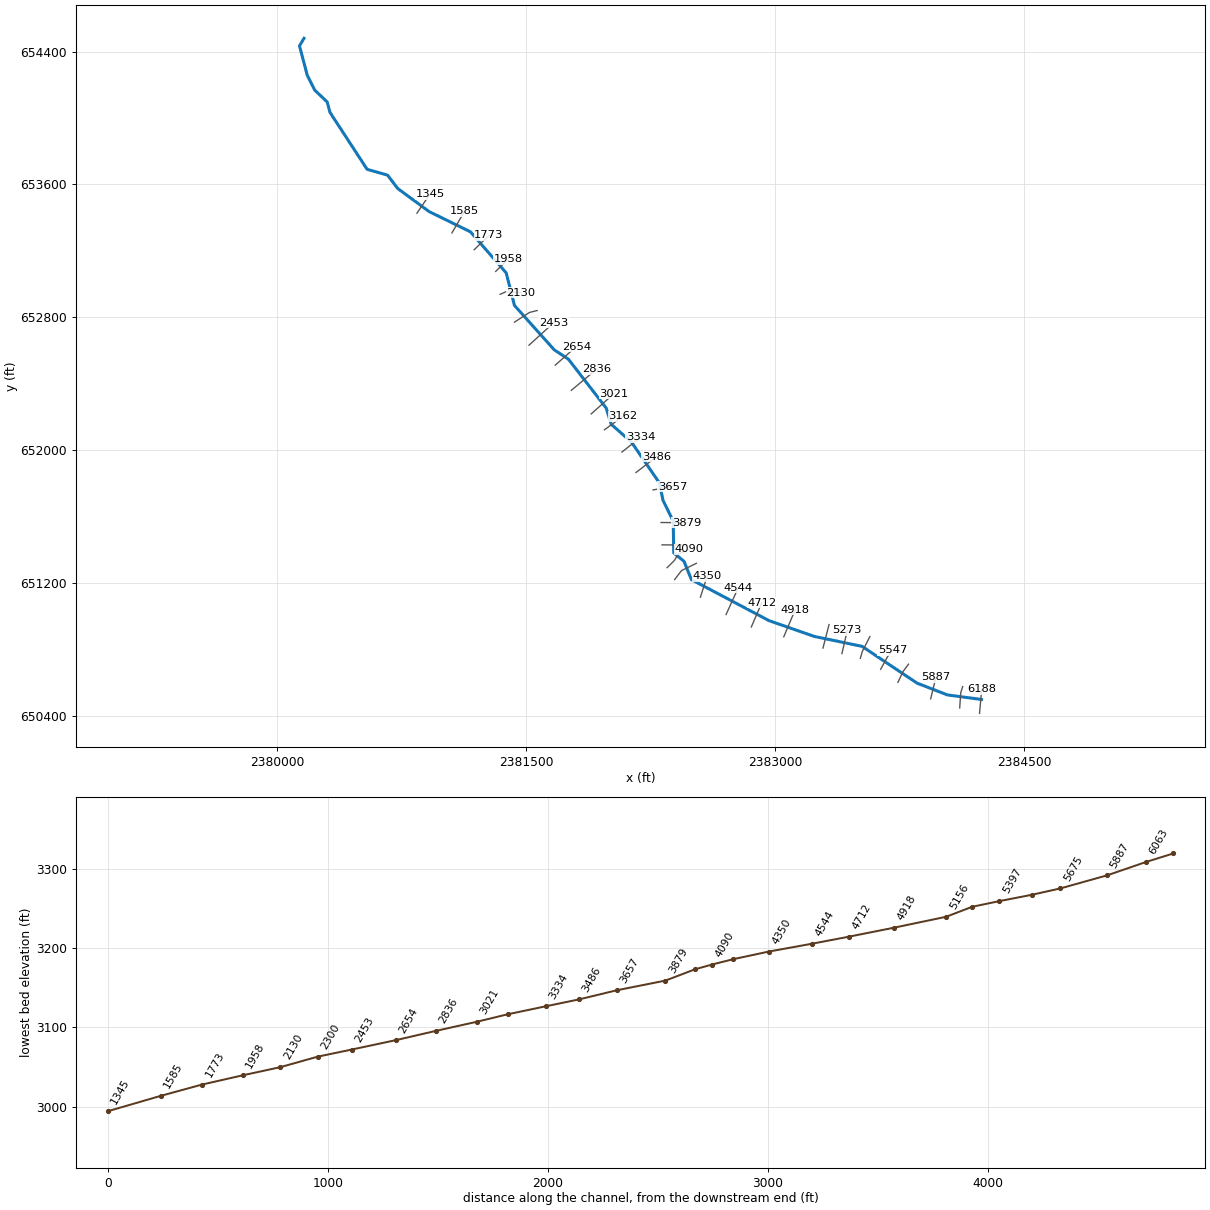
--- UPP2SPRRN.prj (project) ---

Proj Title=UPP2SPRRN
Current Plan=p01
Default Exp/Contr=0,0
English Units
Geom File=g01
Flow File=f01
Plan File=p01
BEGIN DESCRIPTION:
----------MODEL BY WOOD PLC 2022----------
AFH study
Randolph County, WV
HEC-RAS Version: RAS 6.2
Vertical Datum: NAVD88
Projection: NAD 1983 StatePlane West Virginia S FIPS 4702 (US Feet)
Terrain: 1-meter LIDAR (FEMA Region III 3DEP collected 2016-2018)
Land Use: 2019 NLCD
Hydrologic Method:
WV SIR2010-5033 regression equations
Additional Model Notes:
None
END DESCRIPTION:
DSS Export Rating Curves= 0
DSS Export Rating Curve Sorted= 0
DSS Export Volume Flow Curves= 0
DXF OffsetX= 0
DXF OffsetY= 0
DXF ScaleX= 0
DXF ScaleY= 0

--- UPP2SPRRN.p01 (plan) ---

Plan Title=Floodplain
Program Version=6.20
Short Identifier=Floodplain
Geom File=g01
Flow File=f01
Subcritical Flow
K Sum by GR= 0
Std Step Tol= 0.01
Critical Tol= 0.01
Num of Std Step Trials= 20
Max Error Tol= 0.3
Flow Tol Ratio= 0.001
Split Flow NTrial= 30
Split Flow Tol= 0.02
Split Flow Ratio= 0.02
Log Output Level= 0
Friction Slope Method= 1
Unsteady Friction Slope Method= 2
Unsteady Bridges Friction Slope Method= 1
Parabolic Critical Depth
Global Vel Dist= 0 , 0 , 0
Global Log Level= 0
CheckData=True
Encroach Param=-1 ,0,0, 0
Mapping Interval=1HOUR
Computation Time Step Use Courant=        0
Computation Time Step Use Time Series=    0
Computation Time Step Count To Double=0
Computation Time Step Max Doubling=0
Computation Time Step Max Halving=0
Computation Time Step Residence Courant=0
Run HTab= 0
Run UNet= 0
Run Sediment= 0
Run PostProcess= 0
Run WQNet= 0
Run RASMapper=-1
UNET Theta= 0
UNET Theta Warmup= 0
UNET ZTol= 0
UNET ZSATol= 0
UNET MxIter= 0
UNET Max Iter WO Improvement= 0
UNET MaxInSteps= 0
UNET DtIC= 0
UNET DtMin= 0
UNET MaxCRTS= 0
UNET WFStab= 0
UNET SFStab= 0
UNET WFX= 1
UNET SFX= 1
UNET Gravity=32.174
UNET 1D Methodology=Finite Difference
UNET DSS MLevel= 1
UNET Pardiso=0
UNET DZMax Abort= 0
UNET Use Existing IB Tables= 0
UNET Froude Reduction=False
UNET Froude Limit= 0
UNET Froude Power= 0
UNET D1 Cores= 0
UNET WindReference=Eulerian
UNET WindDragFormulation=Hsu (1988)
UNET D2 Coriolis=0
UNET D2 Cores= 0
UNET D2 Theta= 1
UNET D2 Theta Warmup= 1
UNET D2 Z Tol= 0.01
UNET D2 Volume Tol= 0.01
UNET D2 Max Iterations= 20
UNET D2 Equation= 0
UNET D2 RampUpFraction=0.1
UNET D2 TimeSlices= 1
UNET D2 Turbulence Formulation=Non-Conservative (original)
UNET D2 Eddy Viscosity=0.3
UNET D2 Transverse Eddy Viscosity=0.1
UNET D2 Smagorinsky Mixing=0
UNET D2 BCVolumeCheck=0
UNET D2 Cores=0
UNET D2 SolverType=PARDISO (Direct)
UNET D2 Minimum Iterations= 2147483647
UNET D2 Maximum Iterations= 2147483647
UNET D2 Restart Number= 10
UNET D2 Relaxation Coeff=1.3
UNET D2 SOR Precondition Iterations= 10
UNET D2 ILUT Maximum Fill= 8
UNET D2 ILUT Tolerance=1E-08
UNET D1D2 MaxIter= 0
UNET D1D2 ZTol=0.01
UNET D1D2 QTol=0.1
UNET D1D2 MinQTol=1
Write IC File= 0
Write IC File at Fixed DateTime=0
Write IC File at Sim End=0
Echo Input=False
Echo Parameters=False
Echo Output=False
Write Detailed= 0
HDF Write Warmup=0
HDF Write Time Slices=0
HDF Flush=0
HDF Compression= 1
HDF Chunk Size= 1
HDF Spatial Parts= 1
HDF Use Max Rows=0
HDF Fixed Rows= 1
Calibration Method= 0
Calibration Iterations= 20
Calibration Max Change=0.05
Calibration Tolerance=0.2
Calibration Maximum=1.5
Calibration Minimum=0.5
Calibration Optimization Method= 1
WQ AD Non Conservative
WQ ULTIMATE=-1
WQ Max Comp Step=1HOUR
WQ Output Interval=15MIN
WQ Output Selected Increments= 0
WQ Output face flow=0
WQ Output face velocity=0
WQ Output face area=0
WQ Output face dispersion=0
WQ Output cell volume=0
WQ Output cell surface area=0
WQ Output cell continuity=0
WQ Output cumulative cell continuity=0
WQ Output face conc=0
WQ Output face dconc_dx=0
WQ Output face courant=0
WQ Output face peclet=0
WQ Output face adv mass=0
WQ Output face disp mass=0
WQ Output cell mass=0
WQ Output cell source sink temp=0
WQ Output nsm pathways=0
WQ Output nsm derived pathways=0
WQ Create Restart=0
WQ Fixed Restart=0
WQ System Summary=0
WQ Write To DSS=0
Sorting and Armoring Iterations= 10
XS Update Threshold= 0.02
Bed Roughness Predictor= 0
Hydraulics Update Threshold= 0.02
Energy Slope Method= 1
Volume Change Method= 1
Sediment Retention Method= 0
Sediment TS Multiplier= 1
Warm Up Method= 0
XS Weighting Method= 0
Number of US Weighted Cross Sections= 1
Number of DS Weighted Cross Sections= 1
Upstream XS Weight=0
Main XS Weight=1
Downstream XS Weight=0
Number of DS XS's Weighted with US Boundary= 1
Upstream Boundary Weight= 1
Weight of XSs Associated with US Boundary= 0
Number of US XS's Weighted with DS Boundary= 1
Downstream Boundary Weight= 0.5
Weight of XSs Associated with DS Boundary= 0.5
Percentile Method= 0
Sediment Output Level= 3
Mass or Volume Output= 0
Output Increment Type= 1
Profile and TS Output Increment= 1
Transport Output Increment 1
XS Output Flag= 0
XS Output Increment= 10
Read HDF5 Sediment Hotstart= 0
Sediment Hotstart Type= 0
Write Gradation File= 0
Read Gradation Hotstart= 0
Write HDF5 File= 1
Write Binary Output= 1
Write DSS Sediment File= 0
DSS Sediment Output Type= 1
SV Curve= 0
Specific Gage Flag= 0
Subcell Erosion Methods= 0
Subcell Deposition Methods= 0
Advection Scheme= 1
Matrix Solver= 0
Implicit Weighting Factor= 1
Maximum Outer Loop Convergence Iterations= 5
Convergence Maximum Absolute= 0.001
Convergence RMSE= 0.0001
Grain Fractions Max Abs Error= 0.001
Max Subgrid Regions= 1
Max Subgrid Length Scale= 3.402823E+38
Initial Layer Thickness= 3.402823E+38
Min Layer Thickness= 3.402823E+38
Max Layer Thickness= 3.402823E+38
Number of Layers= 5

--- UPP2SPRRN.f01 (steady flow) ---

Flow Title=Flow
Program Version=6.20
Number of Profiles= 1
Profile Names=P100yr
River Rch & RM=UPP2SPRRN,Main            ,6188
     342
River Rch & RM=UPP2SPRRN,Main            ,4544
     384
River Rch & RM=UPP2SPRRN,Main            ,3334
     428
Boundary for River Rch & Prof#=UPP2SPRRN,Main            , 1
Up Type= 0
Dn Type= 3
Dn Slope=0.22584
DSS Import GetInterval= 0
DSS Import GetPeak= 0
DSS Import FillOption= 0

--- UPP2SPRRN.g01 (geometry) ---

Geom Title=Geometry
Program Version=6.20

River Reach=UPP2SPRRN       ,Main
Reach XY= 30
 2384241.3513817650497.3707991952384036.09999711650524.747266619
2383853.43600003      650595.6842383522.08099999650817.229000002
2383234.62299135650877.0477651692382961.94700001650971.979000017
2382494.06100003651219.381999999     2382449.889651329.105000019
2382387.68000001651380.0620000062382384.59899999651571.552000001
2382322.96700004651696.9860000012382300.83100002651802.454999998
2382134.16500005652045.9449999932382010.46700004652155.753000021
2381980.95300002652252.5420000112381753.52200003652546.812999994
2381668.01899998652603.236000016     2381428.436652870.597000003
2381378.52300002653066.7780000122381163.24500003 653314.17400001
2380914.11300004653436.1350000052380725.19500002653575.024000004
2380663.94800004653655.4889999932380540.82000001653690.649000019
2380316.86199999654033.8789999932380300.33499999654096.204999998
 2380225.1467672654167.7048665062380180.27237327654257.300834714
2380133.37331923654434.2949817272380160.54900001654479.577000007

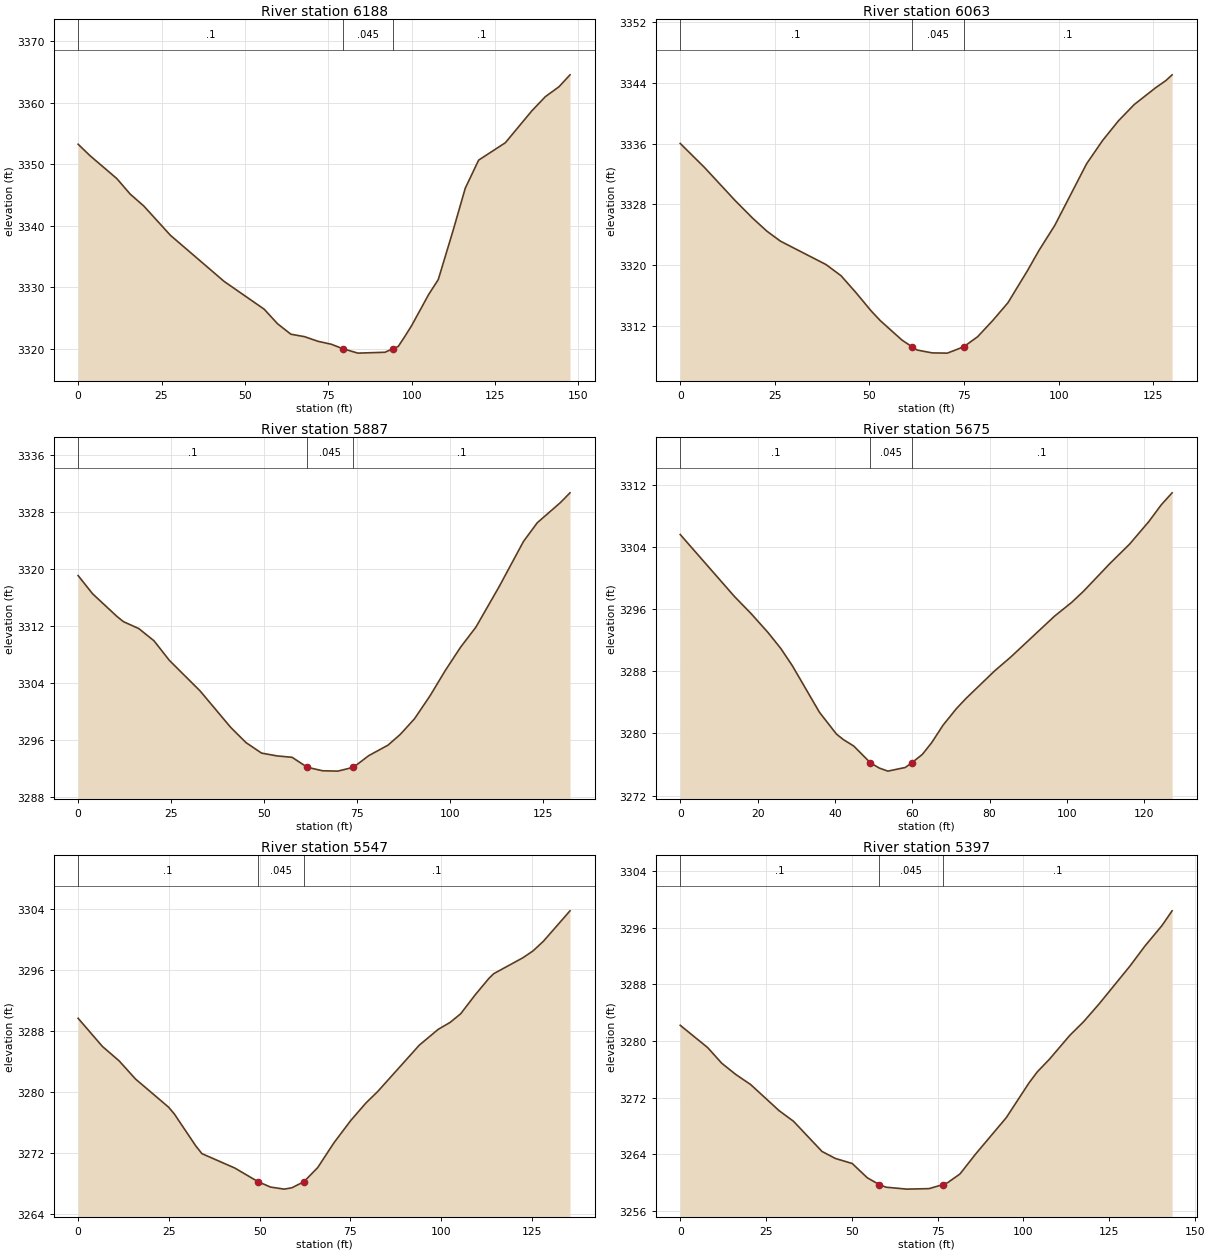
Type RM Length L Ch R = 1 ,6188    ,124.9,125.4,124.9
XS GIS Cut Line= 2
2384229.61733344650413.5959010752384242.85880213650560.533489083
#Sta/Elev= 30
       0 3353.27     3.6 3351.39    11.6 3347.68    15.6 3345.16    19.7 3343.21
    27.7 3338.43    43.8 3330.93    55.8 3326.41    59.8 3324.04    63.8 3322.34
    67.9 3321.94    71.9 3321.19    75.9 3320.71    79.33319.996    83.9 3319.26
      92  3319.4    94.53319.995      96 3320.35    97.8 3321.83     100 3323.73
   105.1 3328.79     108 3331.24   112.5 3339.33   116.1 3346.12   120.1 3350.68
   128.1 3353.51   136.1 3358.73   140.1 3361.01   144.2 3362.63   147.5 3364.57
#Mann= 3, -1 ,  0
       0     0.1       0    79.3   0.045       0    94.5     0.1       0
Bank Sta=79.3,94.5
XS Rating Curve= 0 ,0
Exp/Cntr(USF)=0,0
Exp/Cntr=0.3,0.1

Type RM Length L Ch R = 1 ,6063    ,176.5,175.7,174.1
XS GIS Cut Line= 3
2384110.19663357650446.7546044732384116.42413337650538.321993222
2384128.05179016650574.756270928
#Sta/Elev= 30
       0 3336.02     6.4 3332.86    14.5  3328.5    19.1 3326.19    22.9 3324.46
    26.5 3323.14    38.5 3320.07    42.5 3318.59    46.5 3316.33    50.5 3313.93
    52.9 3312.66    58.6 3310.11    61.33309.214    62.6  3308.8    66.6 3308.42
    70.6 3308.39    74.9 3309.22    78.6 3310.55    82.6 3312.69    86.6 3315.02
    91.8 3319.28    94.8 3321.91      99 3325.23   107.4 3333.34   111.6 3336.39
   115.8 3338.99     120 3341.15   125.7 3343.38   128.4 3344.32     130 3345.06
#Mann= 3, -1 ,  0
       0     0.1       0    61.3   0.045       0    74.9     0.1       0
Bank Sta=61.3,74.9
XS Rating Curve= 0 ,0
Exp/Cntr(USF)=0,0
Exp/Cntr=0.3,0.1

Type RM Length L Ch R = 1 ,5887    ,213.2,212.5,210.7
XS GIS Cut Line= 2
 2383935.3078686650501.342854528 2383966.7716827650629.727398048
#Sta/Elev= 30
       0 3319.06     3.9  3316.5    10.5  3313.3    12.2 3312.59    16.3 3311.63
    20.4 3309.91    24.5 3307.18    32.8 3302.87      41 3297.77    45.1 3295.64
    49.3 3294.16    53.4 3293.77    57.5 3293.57    61.6 3292.17    65.7 3291.68
    69.8 3291.63      74 3292.17    78.1  3293.8    83.3 3295.28    86.6 3296.79
    90.4 3298.97    94.6 3302.21    98.7 3305.76   102.8 3309.02   106.9 3311.82
   113.2 3317.55   119.7 3323.85   123.4 3326.47   129.6 3329.29   132.2 3330.67
#Mann= 3, -1 ,  0
       0     0.1       0    61.6   0.045       0      74     0.1       0
Bank Sta=61.6,74
XS Rating Curve= 0 ,0
Exp/Cntr(USF)=0,0
Exp/Cntr=0.3,0.1

Type RM Length L Ch R = 1 ,5675    ,128,127.4,127.7
XS GIS Cut Line= 3
2383738.01452433650600.6806576332383769.15593846650666.038094427
2383801.84602924650710.054665381
#Sta/Elev= 30
       0 3305.62      14 3297.65    18.3 3295.45    22.7    3293      26 3290.95
      29 3288.72      36 3282.73    40.4 3279.92    42.2 3279.21    44.9 3278.37
    49.23276.211    51.5 3275.54    53.7 3275.15    58.2 3275.62    59.9 3276.23
    62.6  3277.3      65  3278.8      68 3281.09    71.4 3283.19    73.9 3284.51
    81.3 3288.06    85.4 3289.81    96.8 3295.11   101.2 3296.87   104.3 3298.32
   111.1 3301.88   116.2 3304.38   121.2  3307.3   124.4 3309.45   127.2 3310.99
#Mann= 3, -1 ,  0
       0     0.1       0    49.2   0.045       0    59.9     0.1       0
Bank Sta=49.2,59.9
XS Rating Curve= 0 ,0
Exp/Cntr(USF)=0,0
Exp/Cntr=0.3,0.1

Type RM Length L Ch R = 1 ,5547    ,149.7,150.6,150.5
XS GIS Cut Line= 3
2383634.17838669650679.279563113 2383675.1842252650754.456933723
2383705.93860409650793.754195632
#Sta/Elev= 30
       0 3289.67     6.7 3285.97    11.3 3284.08    15.8  3281.7    24.9 3278.01
    26.5 3277.11    32.4 3272.92    34.1  3271.9    43.2    3270    49.6 3268.21
      53 3267.51    56.8 3267.24    58.9 3267.42    62.23268.215      66 3270.07
    70.5 3273.34    75.1 3276.25    79.3 3278.56    82.5 3280.04      94 3286.15
    99.2 3288.22   102.5 3289.14   105.4 3290.27   109.4 3292.76   113.2 3294.93
   114.5 3295.53   122.5 3297.61   125.3 3298.51   128.2  3299.8   135.5 3303.78
#Mann= 3, -1 ,  0
       0     0.1       0    49.6   0.045       0    62.2     0.1       0
Bank Sta=49.6,62.2
XS Rating Curve= 0 ,0
Exp/Cntr(USF)=0,0
Exp/Cntr=0.3,0.1

Type RM Length L Ch R = 1 ,5397    ,121,123.8,125.5
XS GIS Cut Line= 3
 2383511.7675829650745.5204935852383523.97519568650787.774177515
2383569.28039921650876.207636978
#Sta/Elev= 30
       0 3282.22       8 3279.07    12.1 3276.86    16.2 3275.27    20.5 3273.86
    28.8 3270.17      33 3268.67    41.3 3264.41    45.2 3263.42    50.1 3262.71
    54.5 3260.69      583259.728      60 3259.36      66 3259.09    72.5 3259.16
    76.53259.727    77.9    3260    81.5 3261.23      86 3264.01      95 3269.19
   101.6 3274.08     104 3275.63   107.6 3277.45   113.5  3280.8   117.5 3282.72
     122 3285.22     131 3290.57   135.4 3293.42   140.3 3296.27   143.3 3298.38
#Mann= 3, -1 ,  0
       0     0.1       0      58   0.045       0    76.5     0.1       0
Bank Sta=58,76.5
XS Rating Curve= 0 ,0
Exp/Cntr(USF)=0,0
Exp/Cntr=0.3,0.1

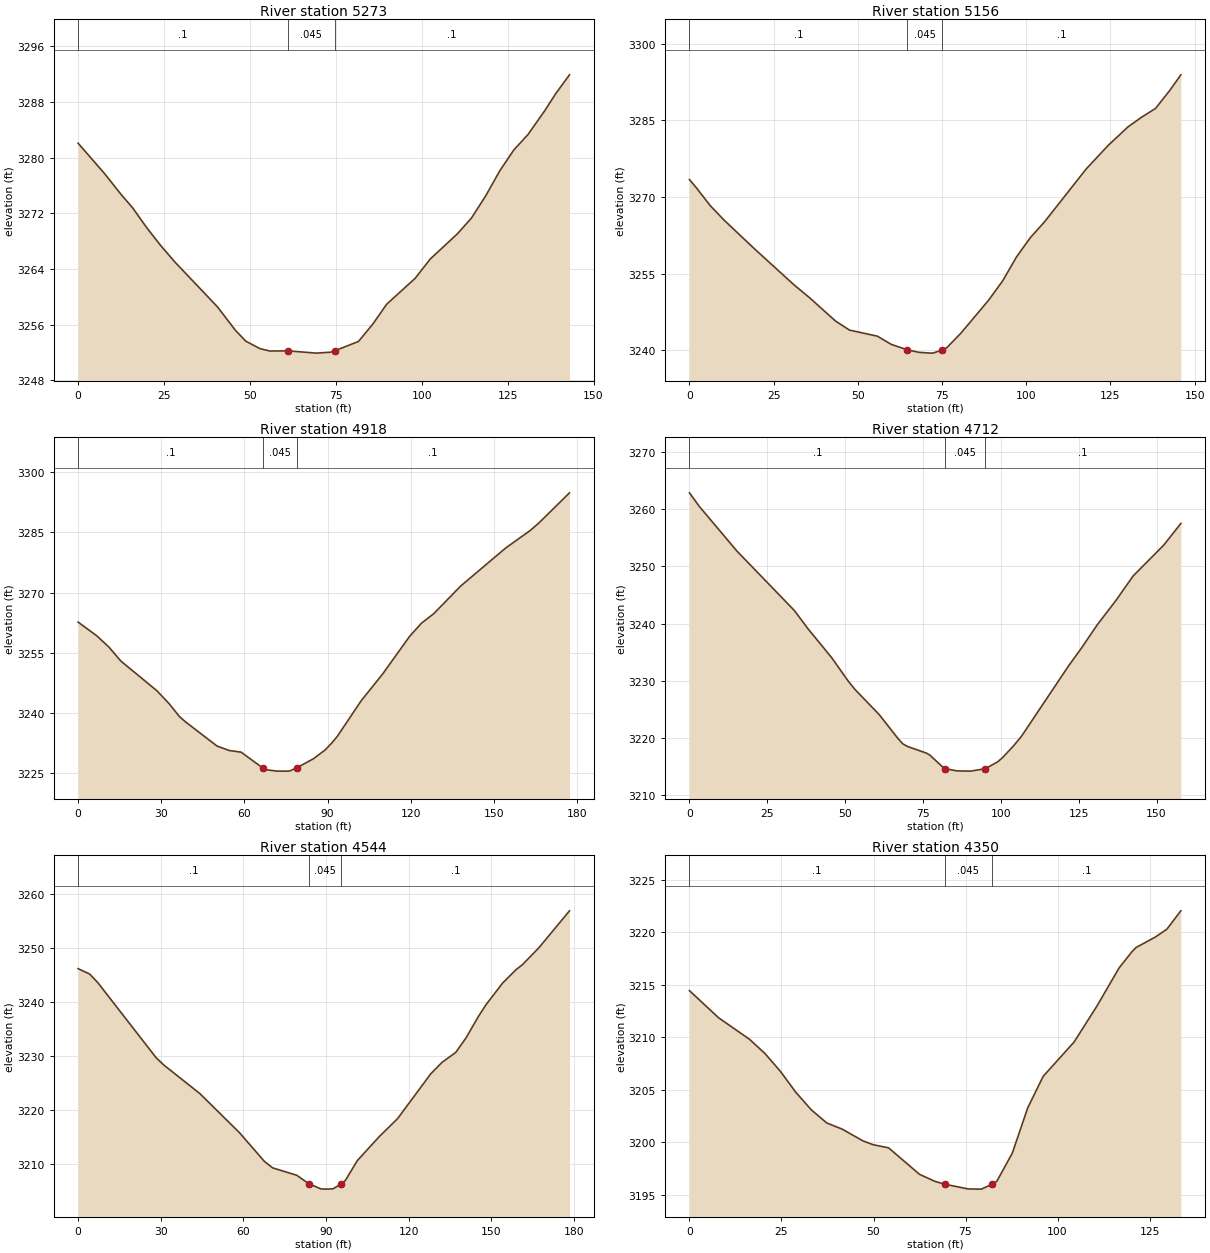
Type RM Length L Ch R = 1 ,5273    ,117.7,117.3,117.2
XS GIS Cut Line= 2
2383400.61956003650773.6784205262383433.08251552650912.927413813
#Sta/Elev= 30
       0 3282.09     7.7 3277.72    12.5 3274.73    15.9 3272.78      20 3269.92
    24.1 3267.34    28.2 3264.99    40.6 3258.54    45.8 3255.18    48.8 3253.63
    52.9 3252.56    55.8 3252.21    61.1 3252.24    69.3 3251.91    73.4 3252.04
   74.62 3252.23    81.6 3253.59    85.8 3256.11    89.8 3258.94    98.1 3262.67
   102.5 3265.45   110.4 3269.07   114.5 3271.35   118.6  3274.5   122.7 3278.11
   126.8 3281.12   130.9 3283.32   135.8 3286.76   139.1 3289.29     143 3291.92
#Mann= 3, -1 ,  0
       0     0.1       0    61.1   0.045       0   74.62     0.1       0
Bank Sta=61.1,74.62
XS Rating Curve= 0 ,0
Exp/Cntr(USF)=0,0
Exp/Cntr=0.3,0.1

Type RM Length L Ch R = 1 ,5156    ,238.6,238,236.9
XS GIS Cut Line= 2
2383286.64578225650807.1759734072383323.21597035650948.406237602
#Sta/Elev= 30
       0 3273.42     2.1 3271.76     6.2 3268.28    10.3 3265.45    19.3 3259.84
      31  3252.8    35.7 3250.23    43.4 3245.66    47.5 3243.91    55.8 3242.71
    59.9 3241.11   64.72 3240.03    68.2 3239.54    71.8 3239.39    72.3  3239.4
    75.1 3240.01    76.4 3240.46    80.6 3243.31    88.8 3249.75      93 3253.56
    97.1 3258.25   101.2 3262.02   105.4 3265.11   117.8  3275.5   124.3  3280.1
   130.2 3283.74   134.3 3285.66   138.4 3287.37   142.6 3290.88   145.9 3293.95
#Mann= 3, -1 ,  0
       0     0.1       0   64.72   0.045       0    75.1     0.1       0
Bank Sta=64.72,75.1
XS Rating Curve= 0 ,0
Exp/Cntr(USF)=0,0
Exp/Cntr=0.3,0.1

Type RM Length L Ch R = 1 ,4918    ,204.7,205.2,204.5
XS GIS Cut Line= 2
2383050.51723013650874.9894115622383119.44592279651038.379199769
#Sta/Elev= 30
       0 3262.68     6.7 3259.28    11.1 3256.47    15.4 3252.99    28.4  3245.6
    32.8  3242.4    36.5  3239.2    38.5 3237.97    50.1 3231.82    54.5  3230.7
    58.8 3230.29    66.63226.364    67.5 3225.94    71.8 3225.56    76.2 3225.56
    78.93226.379    84.9 3228.64    89.2 3230.87    91.5 3232.55    93.5 3234.19
   102.2 3243.15   109.8 3249.67   119.6 3259.11   123.9 3262.41   128.3 3264.76
     138 3271.63   154.3 3281.14     163 3285.42   166.2 3287.32   177.3 3294.87
#Mann= 3, -1 ,  0
       0     0.1       0    66.6   0.045       0    78.9     0.1       0
Bank Sta=66.6,78.9
XS Rating Curve= 0 ,0
Exp/Cntr(USF)=0,0
Exp/Cntr=0.3,0.1

Type RM Length L Ch R = 1 ,4712    ,168.1,168.2,167.8
XS GIS Cut Line= 2
 2382855.1585819650934.2249366022382917.43721545651079.265289004
#Sta/Elev= 30
       0 3262.84     3.2 3260.44    15.2 3252.69    33.7 3242.27      38 3239.14
    45.7 3234.02    51.1 3229.86    53.3  3228.4    60.9 3224.12      67 3219.89
    68.5    3219      70 3218.53    76.1 3217.37    77.2 3217.02    81.6  3214.8
    82.2 3214.65    85.9 3214.26    90.3 3214.22   94.99 3214.64      99 3215.85
   100.5 3216.56     104 3218.59   106.6 3220.29   121.8 3232.65   125.8 3235.65
   130.9 3239.74     137 3244.07   142.5 3248.33   152.3  3253.7   157.8 3257.49
#Mann= 3, -1 ,  0
       0     0.1       0    82.2   0.045       0   94.99     0.1       0
Bank Sta=82.2,94.99
XS Rating Curve= 0 ,0
Exp/Cntr(USF)=0,0
Exp/Cntr=0.3,0.1

Type RM Length L Ch R = 1 ,4544    ,193.7,194.5,195.2
XS GIS Cut Line= 2
2382702.90698501651008.9066366392382776.69737801651171.309566155
#Sta/Elev= 30
       0 3246.23     4.2 3245.23     7.2 3243.61    28.4 3229.66    31.1 3228.36
    44.2 3223.05    58.6 3215.79    67.6 3210.48    70.6 3209.27    79.4 3207.89
    83.73206.343    88.2 3205.35    90.1 3205.32    92.6 3205.38    95.5 3206.31
      97 3206.91   101.4 3210.63   109.4  3215.1     116 3218.41     128 3226.69
   132.1 3228.83   137.1 3230.68   140.9 3233.43   145.3 3237.33   148.1 3239.54
   154.1 3243.54     159 3246.05   161.3 3246.96   167.3 3250.11   178.4 3256.96
#Mann= 3, -1 ,  0
       0     0.1       0    83.7   0.045       0    95.5     0.1       0
Bank Sta=83.7,95.5
XS Rating Curve= 0 ,0
Exp/Cntr(USF)=0,0
Exp/Cntr=0.3,0.1

Type RM Length L Ch R = 1 ,4350    ,166.8,162.7,156.5
XS GIS Cut Line= 2
2382548.41295805651113.6960933612382589.31666417651240.787134054
#Sta/Elev= 30
       0 3214.43     7.9 3211.85    16.3  3209.8    20.5 3208.45    24.7 3206.75
    28.9 3204.75    33.1 3203.08    37.3 3201.83    41.5 3201.24    47.1 3200.13
    49.9 3199.76    54.1 3199.46    62.5 3196.94    66.7 3196.27    69.3    3196
    75.7 3195.55    79.3 3195.53    82.1 3195.98    83.5 3196.27    87.7 3198.95
    91.9 3203.27    96.1 3206.27   104.5 3209.54   110.7 3212.96   116.7 3216.58
   120.2 3218.13   121.3 3218.53   126.6 3219.54   129.7 3220.28   133.5 3222.03
#Mann= 3, -1 ,  0
       0     0.1       0    69.3   0.045       0    82.1     0.1       0
Bank Sta=69.3,82.1
XS Rating Curve= 0 ,0
Exp/Cntr(USF)=0,0
Exp/Cntr=0.3,0.1

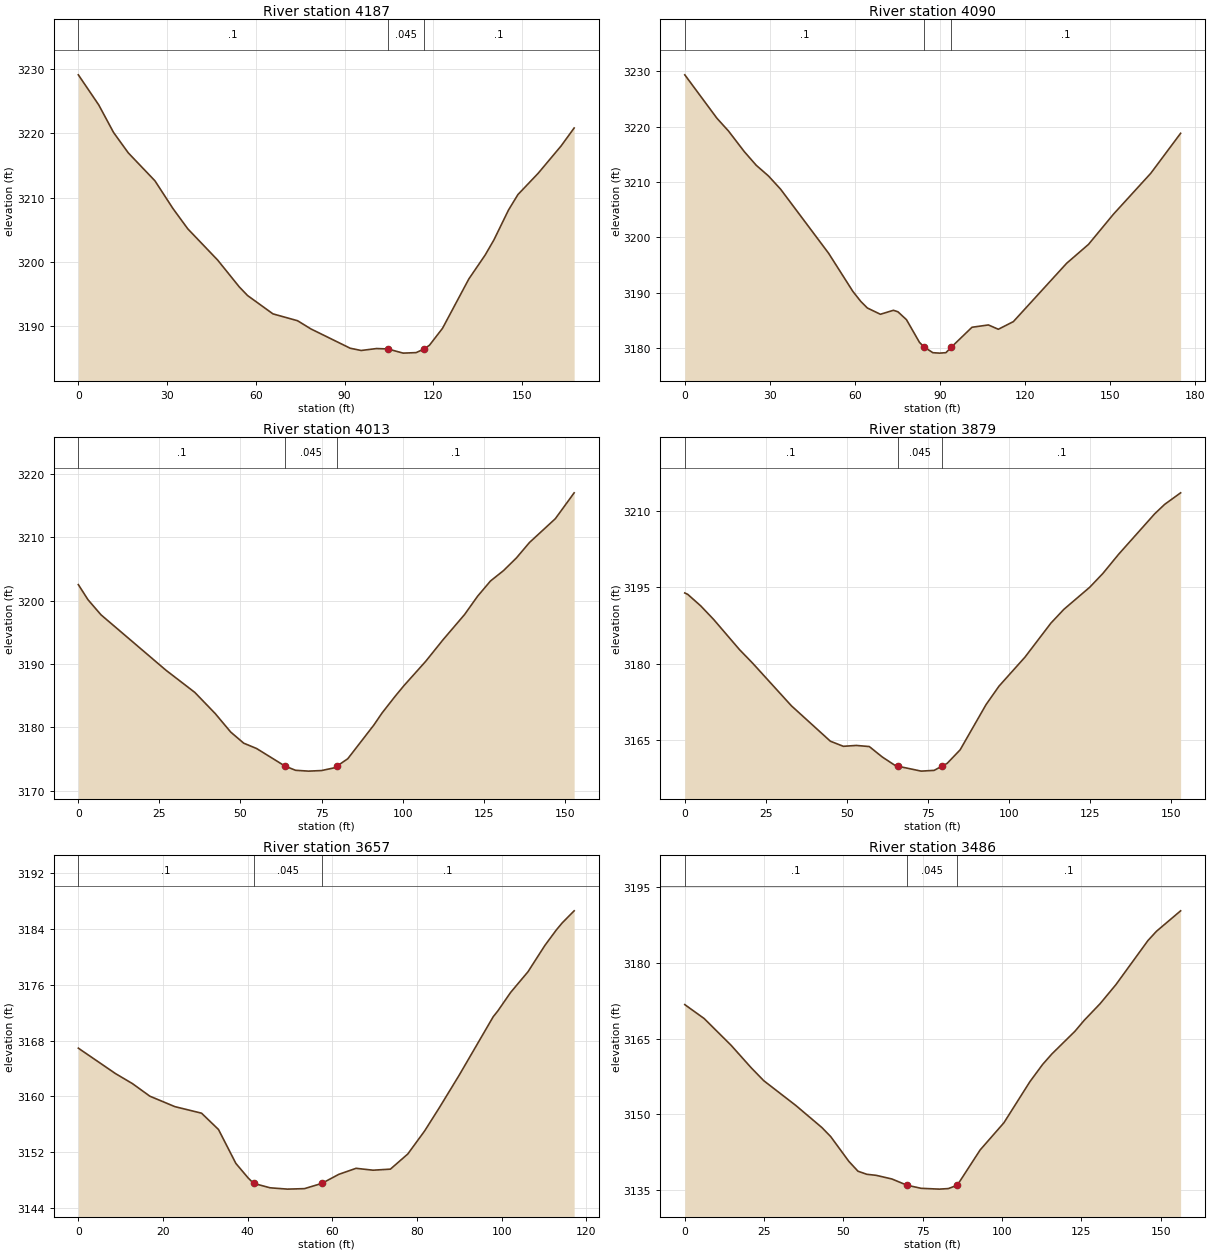
Type RM Length L Ch R = 1 ,4187    ,93.6,96.8,100.2
XS GIS Cut Line= 3
2382393.37344785651219.7110581992382434.37928637651273.531221249
2382524.07955812651317.527068821
#Sta/Elev= 30
       0 3229.05     6.9 3224.38    11.9 3220.11    16.9 3216.93    25.9  3212.6
      32 3208.29      37 3205.15    47.1  3200.3    54.4 3196.14    57.2  3194.8
    65.8 3191.95    74.1 3190.89    78.6 3189.62    91.9 3186.62    95.6 3186.27
   100.8 3186.57   104.6 3186.51   109.8 3185.86   114.2 3185.94  116.87  3186.5
   118.7 3187.09   123.1 3189.71     132 3197.37   137.5 3201.07   140.5 3203.45
   145.4 3208.06   148.6 3210.47   155.4 3213.75   163.2 3218.02   167.6  3220.8
#Mann= 3, -1 ,  0
       0     0.1       0   104.6   0.045       0  116.87     0.1       0
Bank Sta=104.6,116.87
XS Rating Curve= 0 ,0
Exp/Cntr(USF)=0,0
Exp/Cntr=0.3,0.1

Type RM Length L Ch R = 1 ,4090    ,82.6,76.8,71.5
XS GIS Cut Line= 4
   2382348.10211651291.5083713772382391.87777799651334.677447426
 2382412.8078414651370.9847002772382477.74295191651401.046614817
#Sta/Elev= 30
       0 3229.34    11.3 3221.52    15.4  3219.2      21 3215.46    25.2    3213
    29.5 3211.08    33.8 3208.68    50.7 3197.13    59.3 3190.21    62.1  3188.4
    64.4 3187.22      69 3186.09    73.6 3186.81    75.2 3186.53    78.2 3185.11
    82.8    3181    84.53180.145    87.5 3179.15    89.9 3179.07    92.1 3179.15
      943180.137   101.3 3183.74   107.1 3184.16   110.6 3183.38   115.9 3184.76
   134.7  3195.3   142.4 3198.71   151.2 3204.16   164.4 3211.57   174.9 3218.78
#Mann= 3, -1 ,  0
       0     0.1       0    84.5   0.045       0      94     0.1       0
Bank Sta=84.5,94
XS Rating Curve= 0 ,0
Exp/Cntr(USF)=0,0
Exp/Cntr=0.3,0.1

Type RM Length L Ch R = 1 ,4013    ,134.7,134.7,134.8
XS GIS Cut Line= 2
2382317.12755153651428.6491606882382470.04515766651427.367728234
#Sta/Elev= 30
       0 3202.52       3 3200.12       7 3197.75      27 3189.02    35.9 3185.52
    42.2 3182.18      47 3179.25      51  3177.5      55 3176.65    63.73173.894
      67 3173.22      71 3173.09      75 3173.18    79.1 3173.63    79.83173.889
    83.1 3175.05    91.1 3180.34    93.7 3182.29    97.7  3184.9   100.4 3186.57
   107.1  3190.4   112.5 3193.84   119.1 3197.79   123.1 3200.67   127.1 3203.09
   131.1 3204.72   135.1 3206.73   139.1 3209.15   147.1 3212.92   152.9    3217
#Mann= 3, -1 ,  0
       0     0.1       0    63.7   0.045       0    79.8     0.1       0
Bank Sta=63.7,79.8
XS Rating Curve= 0 ,0
Exp/Cntr(USF)=0,0
Exp/Cntr=0.3,0.1

Type RM Length L Ch R = 1 ,3879    ,219.6,221.2,221.5
XS GIS Cut Line= 2
2382311.31295046651563.2543839952382464.23055659651561.972951541
#Sta/Elev= 30
       0 3193.88      .9 3193.61     4.9 3191.35     8.9 3188.67    16.9 3182.72
    20.9 3180.09    32.9 3171.68    44.9 3164.73    48.9 3163.73    52.9  3163.9
    56.9 3163.68    60.9 3161.63    64.9 3159.95    65.63159.833    72.9 3158.85
    76.9    3159    79.43159.856    80.9 3160.37    84.9 3163.03    92.9 3171.93
    96.9 3175.56   104.9 3181.26   112.9 3187.95   116.9 3190.66   124.9 3195.02
   128.9  3197.7   133.8  3201.5   144.9 3209.44     148 3211.31   152.9 3213.57
#Mann= 3, -1 ,  0
       0     0.1       0    65.6   0.045       0    79.4     0.1       0
Bank Sta=65.6,79.4
XS Rating Curve= 0 ,0
Exp/Cntr(USF)=0,0
Exp/Cntr=0.3,0.1

Type RM Length L Ch R = 1 ,3657    ,167.5,171.6,175.3
XS GIS Cut Line= 2
2382263.51529873651759.5734668742382378.91270004651779.202372501
#Sta/Elev= 30
       0  3166.9     8.8 3163.24    12.8  3161.8    16.9    3160    22.8  3158.5
    29.1 3157.56    33.1 3155.22    37.2 3150.35    40.1 3148.26    41.43147.477
    45.3 3146.84    49.4 3146.65    53.4 3146.72    57.5 3147.47    61.5 3148.77
    65.6 3149.64    69.6 3149.37    73.7 3149.52    77.8 3151.69    81.8 3155.02
    85.2 3158.29    89.9 3162.97      98 3171.43    99.1 3172.27   102.1 3174.91
   106.2 3177.88   110.2 3181.67   112.9 3183.89   114.3 3184.91   117.1 3186.63
#Mann= 3, -1 ,  0
       0     0.1       0    41.4   0.045       0    57.5     0.1       0
Bank Sta=41.4,57.5
XS Rating Curve= 0 ,0
Exp/Cntr(USF)=0,0
Exp/Cntr=0.3,0.1

Type RM Length L Ch R = 1 ,3486    ,151.9,151.4,151.3
XS GIS Cut Line= 2
 2382160.4049892651864.4214672232382284.36484143651959.688607626
#Sta/Elev= 30
       0 3171.75     6.1 3168.99    14.6 3163.68    20.9 3159.24    24.9 3156.65
      35 3151.74    43.2 3147.37      46 3145.56    51.7 3140.66    54.6 3138.69
    57.4 3138.08    60.3 3137.88    65.3 3137.15      703135.926    74.5  3135.3
    80.2 3135.14    83.1 3135.25    85.93135.918    93.1 3142.91   100.6 3148.31
   108.8 3156.47   112.8 3159.88   115.7 3161.95     123 3166.47   125.9 3168.63
   130.9 3171.92   135.9 3175.71     146 3184.46   148.7 3186.31   156.3 3190.36
#Mann= 3, -1 ,  0
       0     0.1       0      70   0.045       0    85.9     0.1       0
Bank Sta=70,85.9
XS Rating Curve= 0 ,0
Exp/Cntr(USF)=0,0
Exp/Cntr=0.3,0.1

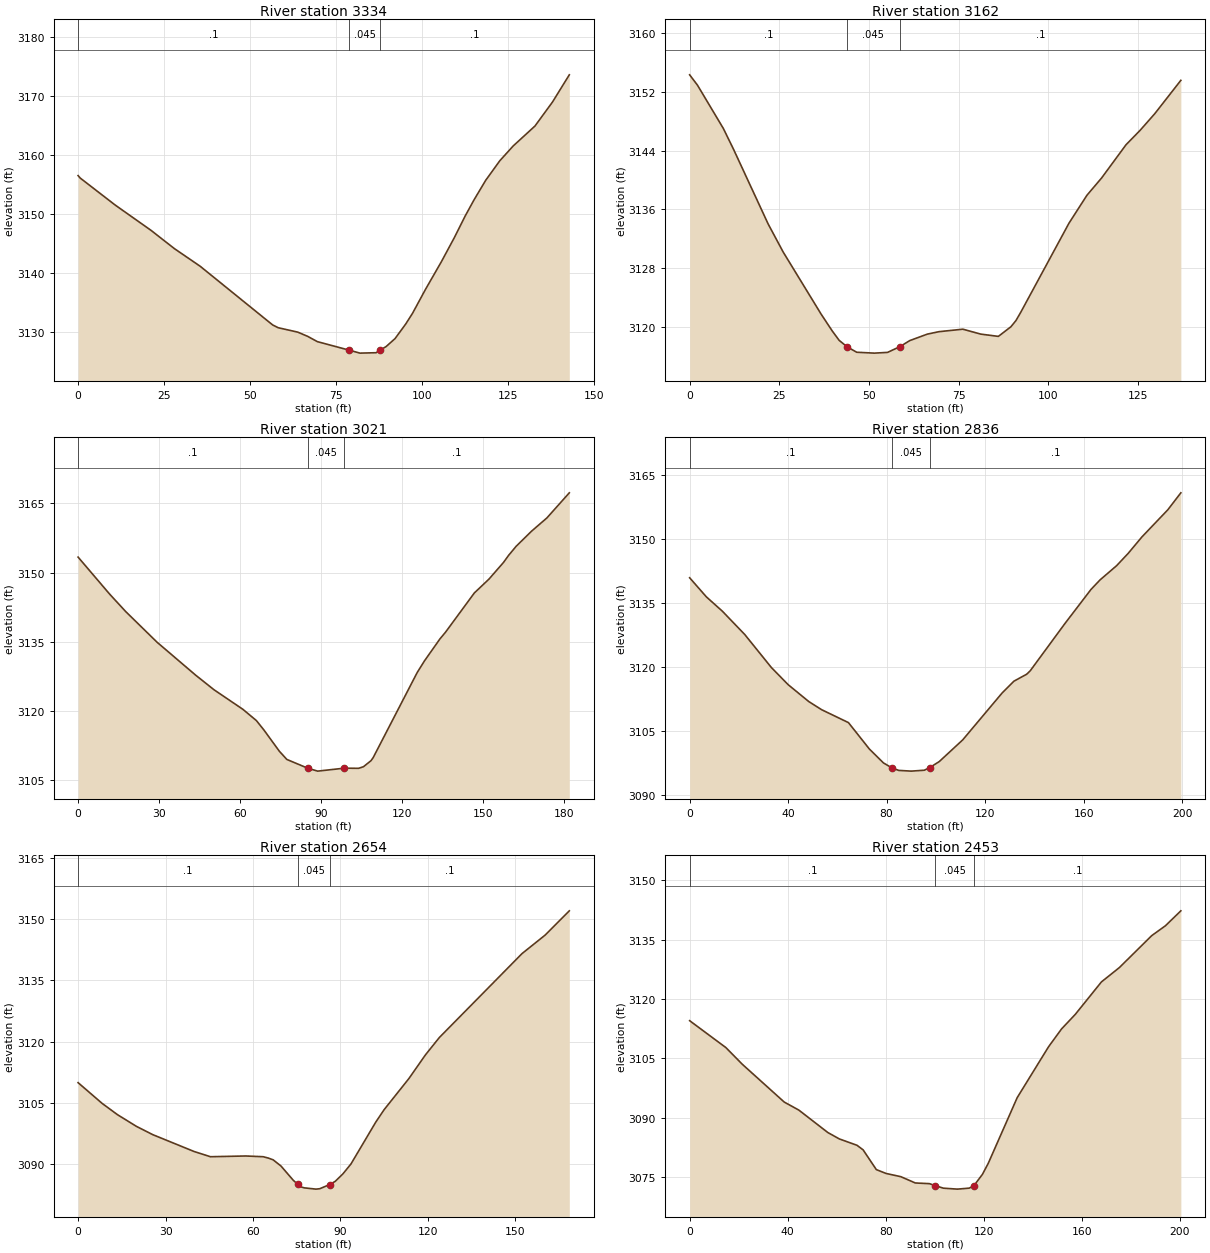
Type RM Length L Ch R = 1 ,3334    ,174.3,172.3,172.2
XS GIS Cut Line= 2
2382075.69966733651987.8645275162382188.00005643 652076.18427221
#Sta/Elev= 30
       0 3156.56      .6 3156.15    10.8 3151.56    21.2 3147.28      28 3144.18
    35.5 3141.19    56.6 3131.23    58.2 3130.76    63.9 3130.01    66.8 3129.29
    69.6  3128.4   78.81 3126.96      82 3126.45    86.7 3126.52   87.86 3126.97
    89.6 3127.56    92.2 3128.91    95.3 3131.38    97.3 3133.21     101  3137.2
   105.7 3141.97   109.5 3146.09   112.6  3149.7   115.2 3152.46   118.6 3155.78
   122.7 3159.09   126.6  3161.6   132.9 3164.96     138 3169.03   142.9 3173.65
#Mann= 3, -1 ,  0
       0     0.1       0   78.81   0.045       0   87.86     0.1       0
Bank Sta=78.81,87.86
XS Rating Curve= 0 ,0
Exp/Cntr(USF)=0,0
Exp/Cntr=0.3,0.1

Type RM Length L Ch R = 1 ,3162    ,139.8,140.9,141
XS GIS Cut Line= 2
2381970.41352671652121.8790536152382081.43890099652202.159758029
#Sta/Elev= 30
       0 3154.32     2.2  3152.9     9.4 3147.01    12.2 3144.22    21.9    3134
    26.1 3130.17    36.7  3121.7    39.8 3119.41    41.7 3118.15    43.93117.275
    46.6 3116.53    51.5 3116.41    55.2 3116.51    58.63117.282    61.4 3118.12
    66.3    3119    69.5 3119.33    76.2 3119.67    81.2    3119    86.1 3118.69
    89.6    3120      91 3120.84    92.4 3122.02   105.8 3134.11   110.8 3137.91
   114.9 3140.27   121.7 3144.79   125.6 3146.74   129.7 3149.01     137 3153.57
#Mann= 3, -1 ,  0
       0     0.1       0    43.9   0.045       0    58.6     0.1       0
Bank Sta=43.9,58.6
XS Rating Curve= 0 ,0
Exp/Cntr(USF)=0,0
Exp/Cntr=0.3,0.1

Type RM Length L Ch R = 1 ,3021    ,185.3,185.2,184.8
XS GIS Cut Line= 2
2381890.57596154652217.4256515382382026.40780162652338.734590475
#Sta/Elev= 30
       0 3153.34    11.6 3145.38    17.6 3141.56    29.3 3134.87    43.5 3127.78
    50.4 3124.57    61.1 3120.33    66.1 3117.89    68.9 3115.84    74.6 3111.25
    77.4 3109.46    85.13107.572    88.8 3106.93    98.7 3107.57     104 3107.54
   105.8 3107.89   108.6  3109.2   109.4 3109.87   125.7  3128.3   128.4 3130.83
   134.1 3135.57   136.2 3137.05   146.9 3145.57   152.3 3148.56   157.7 3152.18
   159.6 3153.72   162.4 3155.69   168.1 3158.96   173.8 3161.84   182.1 3167.28
#Mann= 3, -1 ,  0
       0     0.1       0    85.1   0.045       0    98.7     0.1       0
Bank Sta=85.1,98.7
XS Rating Curve= 0 ,0
Exp/Cntr(USF)=0,0
Exp/Cntr=0.3,0.1

Type RM Length L Ch R = 1 ,2836    ,182.2,182.2,182
XS GIS Cut Line= 2
2381770.97810576652359.5896041912381924.26927586652487.340252268
#Sta/Elev= 30
       0 3140.82     6.8 3136.34    13.3 3132.98    22.4 3127.51    33.2 3119.78
      40 3115.77    48.4  3111.8    53.6  3109.9    64.5 3106.87      73 3100.68
    78.7 3097.43      823096.315    84.9 3095.67      90  3095.5    95.3 3095.71
    97.53096.325   101.4 3097.75   110.9 3102.82   126.9 3113.81   131.7 3116.58
   136.9 3118.22   138.3    3119   152.4 3130.08     163 3138.08   166.7 3140.33
   173.4 3143.65   178.1 3146.53   183.7  3150.4   194.2 3156.75   199.5 3160.73
#Mann= 3, -1 ,  0
       0     0.1       0      82   0.045       0    97.5     0.1       0
Bank Sta=82,97.5
XS Rating Curve= 0 ,0
Exp/Cntr(USF)=0,0
Exp/Cntr=0.3,0.1

Type RM Length L Ch R = 1 ,2654    ,201,201.2,201
XS GIS Cut Line= 2
2381674.04742124652511.1257675862381800.30346365652622.669470348
#Sta/Elev= 30
       0 3109.92     8.2 3104.86    13.5 3102.07      20  3099.2    25.6 3097.17
    39.8 3093.03    45.4 3091.75    57.5 3091.93    63.5 3091.75    65.3 3091.41
    66.9 3090.99    69.6 3089.47    73.8 3085.98    75.43084.949    76.6 3084.32
    77.6 3084.11    81.6  3083.8    82.9  3083.9    86.33084.917    88.2 3085.71
    90.8 3087.51    93.6 3089.97   102.1 3100.23     105 3103.32   113.5 3110.95
   119.1 3116.69   123.9 3120.98   152.3  3141.6   160.2 3146.12   168.5 3152.08
#Mann= 3, -1 ,  0
       0     0.1       0    75.4   0.045       0    86.3     0.1       0
Bank Sta=75.4,86.3
XS Rating Curve= 0 ,0
Exp/Cntr(USF)=0,0
Exp/Cntr=0.3,0.1

Type RM Length L Ch R = 1 ,2453    ,154.8,152.8,151.4
XS GIS Cut Line= 2
2381515.77327768652631.2070487442381664.11069118652766.079550444
#Sta/Elev= 30
       0 3114.52    14.8 3107.71    21.5 3103.49    38.6 3093.94    44.6 3091.89
    56.4 3086.23    61.1 3084.61    68.3    3083    70.8 3081.85    76.2 3076.85
    80.2 3075.87    86.2 3075.06    92.1 3073.47    97.9 3073.29   100.33072.779
   103.6 3072.15   109.3 3071.91   114.1 3072.16     116 3072.76   119.5 3075.64
   121.9 3078.45   133.7 3095.05   146.5 3107.92   151.8 3112.43   157.4 3116.11
   168.1 3124.34   175.4 3127.95   188.6 3136.03   194.2 3138.53   200.5 3142.31
#Mann= 3, -1 ,  0
       0     0.1       0   100.3   0.045       0     116     0.1       0
Bank Sta=100.3,116
XS Rating Curve= 0 ,0
Exp/Cntr(USF)=0,0
Exp/Cntr=0.3,0.1

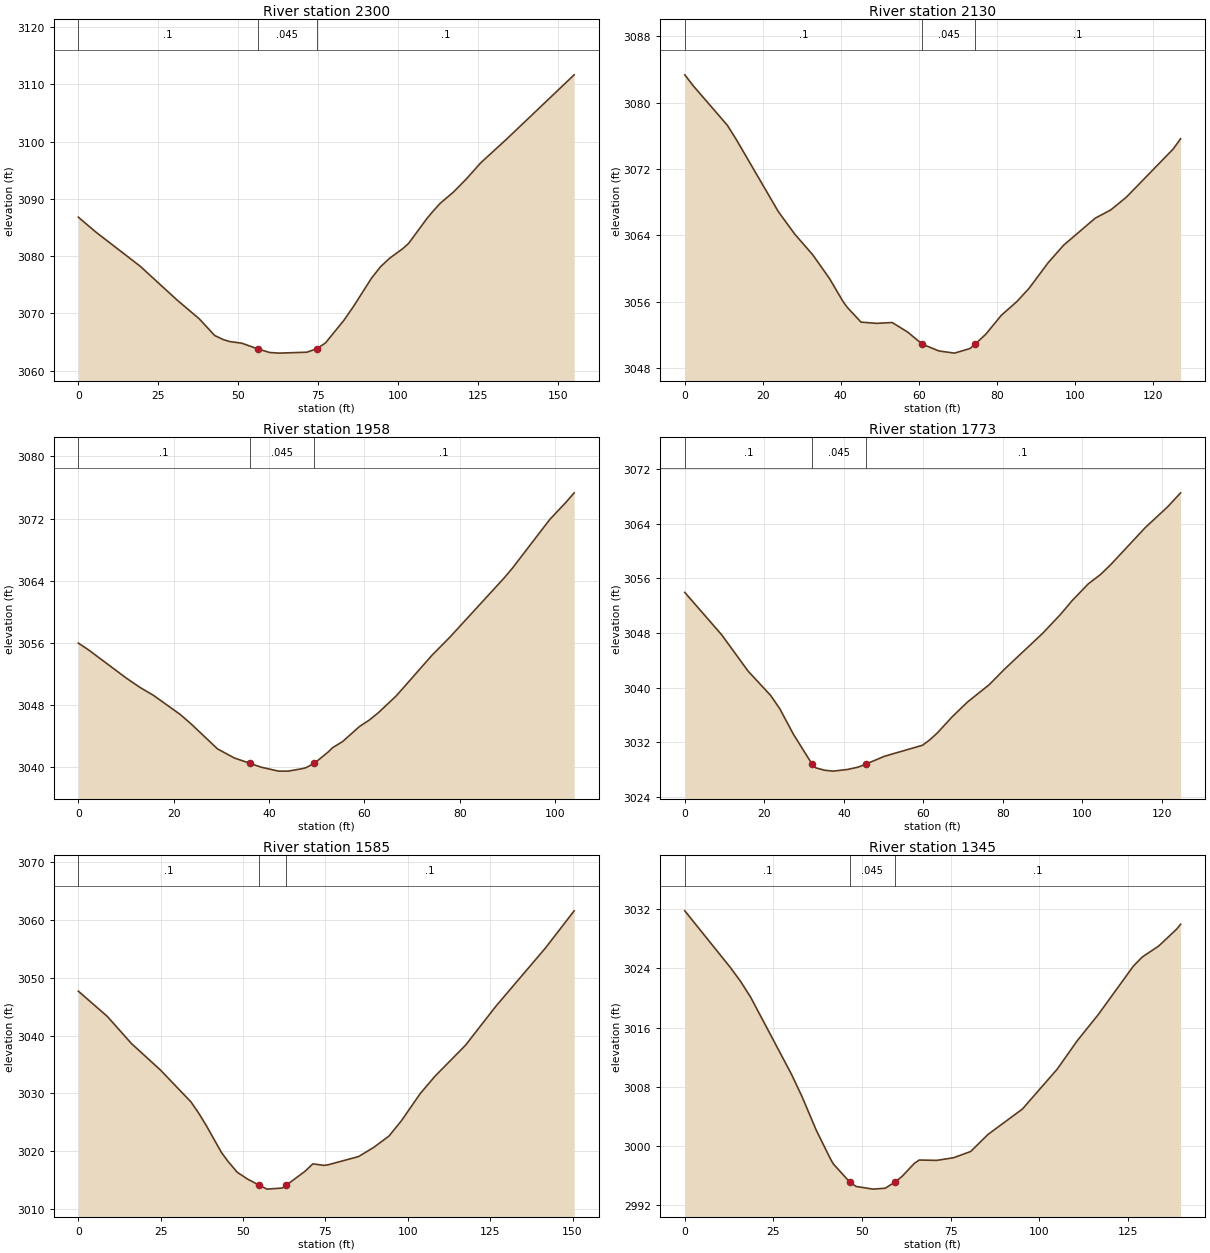
Type RM Length L Ch R = 1 ,2300    ,174.8,170.3,166.2
XS GIS Cut Line= 3
2381428.41876821652770.2462988512381518.40121113 652828.29138507
2381564.76570064652840.018044061
#Sta/Elev= 30
       0 3086.82     5.4 3084.25    19.3 3078.26    30.9 3072.32    37.8 3069.05
    42.6 3066.15    45.3 3065.43    47.3 3065.09    51.1  3064.8      563063.819
    59.8 3063.18    62.7 3063.07    71.4 3063.23    74.53063.843    77.2 3064.84
      83 3068.83    85.9 3071.17    91.6 3076.17    94.5 3078.22    97.4 3079.71
   101.3 3081.29   103.2 3082.25   108.9 3086.58   110.7 3087.78     113 3089.21
   117.2 3091.21   121.3 3093.54   125.7  3096.3   133.7  3100.4   154.9 3111.68
#Mann= 3, -1 ,  0
       0     0.1       0      56   0.045       0    74.5     0.1       0
Bank Sta=56,74.5
XS Rating Curve= 0 ,0
Exp/Cntr(USF)=0,0
Exp/Cntr=0.3,0.1

Type RM Length L Ch R = 1 ,2130    ,165.5,171.3,176.8
XS GIS Cut Line= 3
2381342.16153435652937.8538598492381376.37578086652952.846619556
2381466.11876703652948.019890647
#Sta/Elev= 30
       0 3083.35     2.2 3082.01    10.9 3077.28    13.2 3075.56      24 3066.86
    28.2 3064.15    32.8 3061.67    37.1 3058.81    40.6 3056.02    41.7 3055.31
    45.2 3053.54    49.2 3053.39    53.2 3053.49    57.2 3052.33    60.93050.884
    65.2 3050.06    69.2  3049.8    73.2 3050.36    74.43050.854    77.2 3052.07
    81.2 3054.36    85.2 3056.02    88.3  3057.6    93.2 3060.69    97.2 3062.82
   105.3 3066.07   109.3 3067.07   113.3 3068.61   125.3 3074.41   127.2 3075.65
#Mann= 3, -1 ,  0
       0     0.1       0    60.9   0.045       0    74.4     0.1       0
Bank Sta=60.9,74.4
XS Rating Curve= 0 ,0
Exp/Cntr(USF)=0,0
Exp/Cntr=0.3,0.1

Type RM Length L Ch R = 1 ,1958    ,185.4,185.6,185.5
XS GIS Cut Line= 2
2381315.36308075653075.7058806852381389.41934923653148.792526525
#Sta/Elev= 30
       0 3055.97     2.1 3055.12    10.1 3051.45    12.9 3050.28    15.8 3049.23
    21.4 3046.77    23.6  3045.6    29.2 3042.35    32.7 3041.19      363040.491
    38.4 3039.99      42 3039.49      44 3039.49    46.9  3039.8    47.7 3039.92
    49.53040.496    52.5    3042    53.3  3042.5    55.4 3043.28      59 3045.25
      61 3046.05      63 3047.05    66.7 3049.19    74.2 3054.42      78 3056.78
    89.3 3064.35    91.1 3065.66    98.9  3071.9   102.3 3074.11     104 3075.32
#Mann= 3, -1 ,  0
       0     0.1       0      36   0.045       0    49.5     0.1       0
Bank Sta=36,49.5
XS Rating Curve= 0 ,0
Exp/Cntr(USF)=0,0
Exp/Cntr=0.3,0.1

Type RM Length L Ch R = 1 ,1773    ,186.5,188.2,188.9
XS GIS Cut Line= 2
2381185.55956654653206.0130755972381274.46953706653293.393298303
#Sta/Elev= 30
       0 3053.94     9.3 3047.72    15.9 3042.44    21.6 3038.86    23.9 3036.91
    27.3  3033.2      323028.829      33 3028.26    35.2 3027.92    37.3 3027.79
    40.9 3028.03    43.7 3028.39    45.5 3028.81    50.2 3029.96    59.8 3031.58
    61.6 3032.36    63.5 3033.37    67.3 3035.77      71 3037.85    76.6 3040.46
    80.5 3042.76    90.1 3048.01    94.6 3050.79    97.4 3052.73   101.5  3055.2
   104.6 3056.58   107.2 3058.05   115.8 3063.42   121.4 3066.44   124.7 3068.51
#Mann= 3, -1 ,  0
       0     0.1       0      32   0.045       0    45.5     0.1       0
Bank Sta=32,45.5
XS Rating Curve= 0 ,0
Exp/Cntr(USF)=0,0
Exp/Cntr=0.3,0.1

Type RM Length L Ch R = 1 ,1585    ,240.2,239.8,239.1
XS GIS Cut Line= 2
2381051.75096956653307.646461289 2381127.5037898653437.744470626
#Sta/Elev= 30
       0 3047.66     8.8  3043.3    16.1 3038.63    24.9 3034.06    34.2 3028.53
    36.5 3026.63    38.8  3024.5    43.4 3019.85    45.3 3018.37    48.2 3016.41
    51.2 3015.27   54.85 3014.16    57.3 3013.48    61.9 3013.67    62.9 3013.95
   63.11 3014.16    68.7 3016.51    71.2 3017.84    74.6 3017.58    75.8 3017.68
    85.1 3019.11    89.7  3020.7    94.3 3022.65      98 3025.24   103.8 3029.99
   108.2 3032.94   117.5 3038.31   126.7 3045.03   141.8 3055.12   150.5 3061.53
#Mann= 3, -1 ,  0
       0     0.1       0   54.85   0.045       0   63.11     0.1       0
Bank Sta=54.85,63.11
XS Rating Curve= 0 ,0
Exp/Cntr(USF)=0,0
Exp/Cntr=0.3,0.1

Type RM Length L Ch R = 1 ,1345    ,101.2,101.1,101.6
XS GIS Cut Line= 2
2380841.03272161 653426.492871462380919.68000392653542.125956277
#Sta/Elev= 30
       0 3031.77    12.9 3024.09    15.7 3022.26    18.6 3020.08    30.1 3009.68
      33 3006.74    37.1 3002.11    41.1 2998.24    41.9 2997.58    46.52995.152
    48.3 2994.55    53.1 2994.19    56.5 2994.31    59.32995.147    61.3 2995.93
    64.7 2997.66    66.1 2998.12      71 2998.07    75.8 2998.43    80.6 2999.27
    85.5 3001.58    95.2 3005.01     105 3010.39   110.7 3014.26   116.5 3017.71
   126.5 3024.32     129 3025.54   133.6 3027.01   138.7 3029.31   139.8 3029.96
#Mann= 3, -1 ,  0
       0     0.1       0    46.5   0.045       0    59.3     0.1       0
Bank Sta=46.5,59.3
XS Rating Curve= 0 ,0
Exp/Cntr(USF)=0,0
Exp/Cntr=0.3,0.1