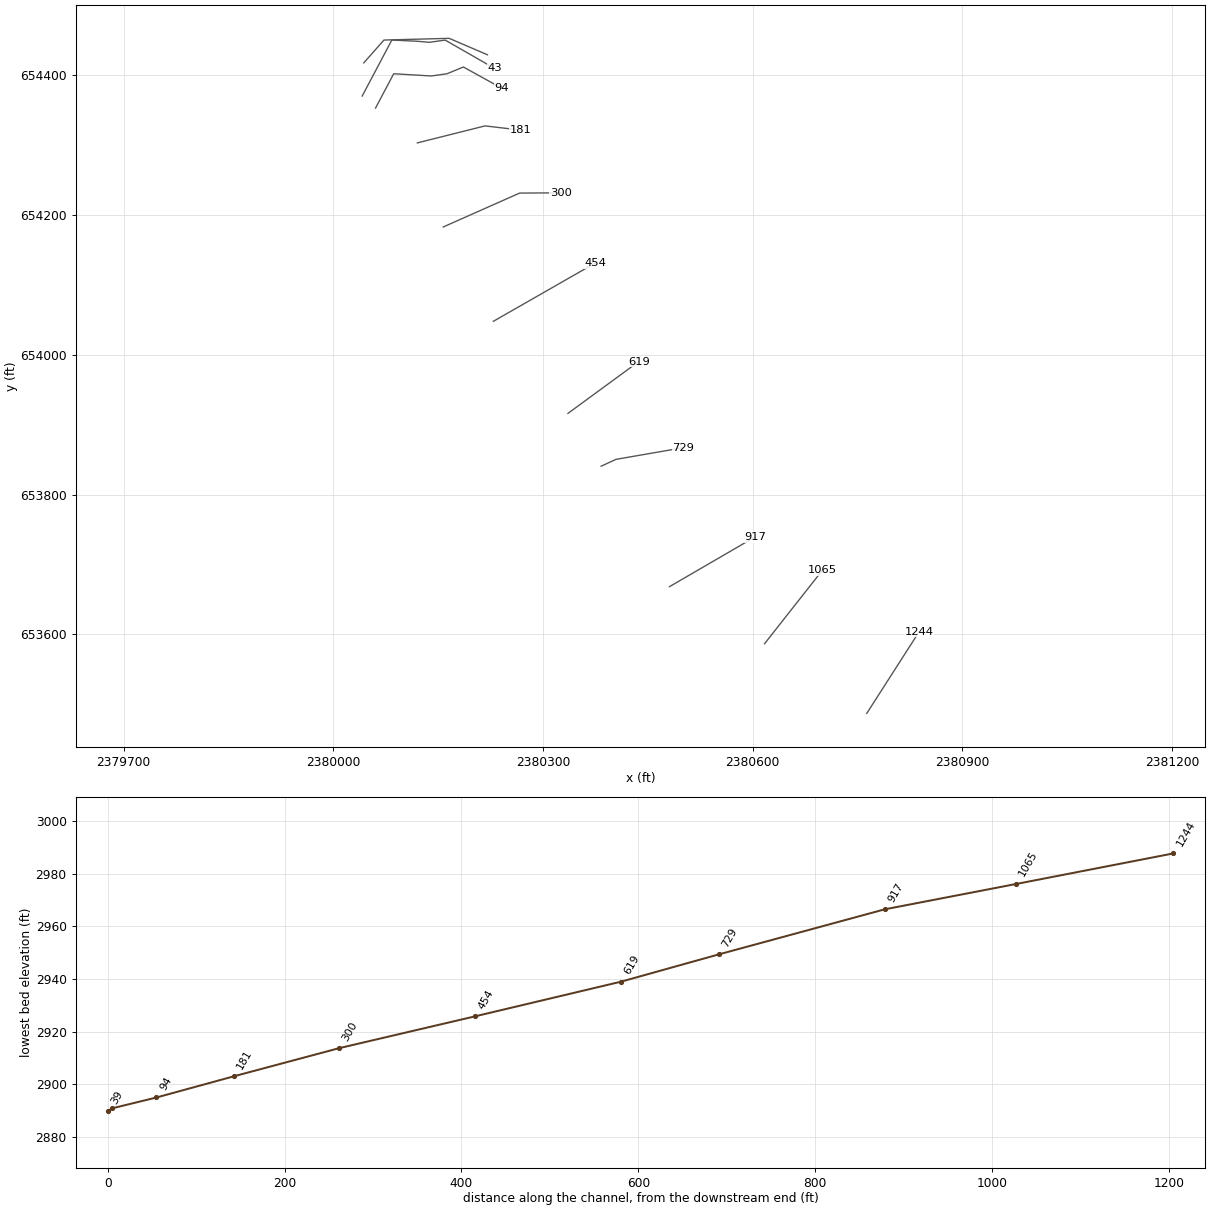
HEC-RAS study UPP2SPRRN.prj: UPP2SPRRN

--- UPP2SPRRN.g01 (geometry) --- (continued)

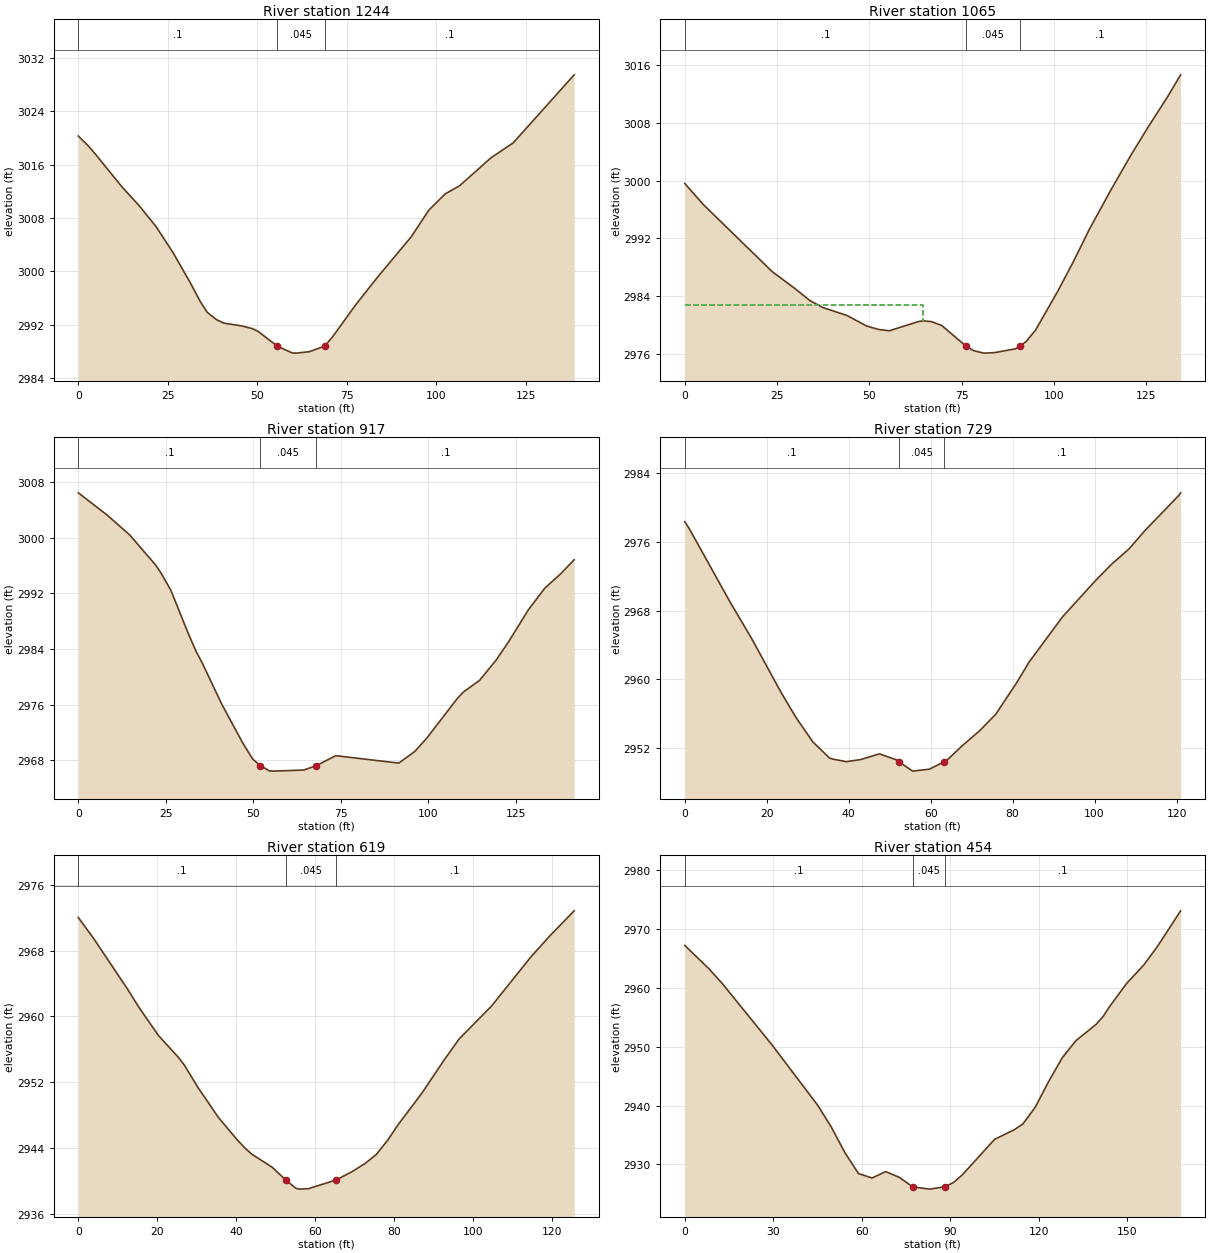
Type RM Length L Ch R = 1 ,1244    ,178,178.3,176.8
XS GIS Cut Line= 2
2380763.34254656653486.8980688652380838.09277302653603.508422139
#Sta/Elev= 30
       0  3020.3     2.7 3018.87     5.1 3017.37    12.2 3012.66      17 3009.84
    21.7 3006.72    26.5 3002.76    31.2 2998.35    34.1 2995.42      36 2993.84
    38.6 2992.73    40.7 2992.21    45.7 2991.79    48.6 2991.39    50.2 2990.98
    55.6 2988.76    59.7 2987.75    60.8 2987.71    64.5 2987.92    68.8 2988.76
      71 2990.14    77.5 2994.98    83.5 2999.06      93 3005.18    97.9 3009.17
   102.5 3011.62   106.5 3012.84   115.2    3017   121.5 3019.29   138.5 3029.49
#Mann= 3, -1 ,  0
       0     0.1       0    55.6   0.045       0    68.8     0.1       0
Bank Sta=55.6,68.8
XS Rating Curve= 0 ,0
Exp/Cntr(USF)=0,0
Exp/Cntr=0.3,0.1

Type RM Length L Ch R = 1 ,1065    ,153.2,148.2,146.7
XS GIS Cut Line= 2
2380617.03273395653586.5263211872380700.14490934653692.081267779
#Sta/Elev= 30
       0 2999.59     5.1 2996.63    23.7 2987.36    29.8 2985.04    33.9 2983.35
    37.4 2982.39    43.9  2981.3    49.2 2979.84    52.5 2979.35    55.4 2979.17
    63.3 2980.45    64.5 2980.54    66.8 2980.44    69.6  2979.9    76.2 2977.03
    78.2 2976.42      81 2976.07    83.9 2976.14    89.6 2976.67    90.72977.018
    92.4 2977.65      95 2979.26     101 2984.63   105.2  2988.7   109.5 2993.16
   115.4 2998.68   120.9 3003.58   125.6  3007.5   130.7 3011.56   134.3 3014.66
#Mann= 3, -1 ,  0
       0     0.1       0    76.2   0.045       0    90.7     0.1       0
#XS Ineff= 2 , 0
           64.58 2982.69
Permanent Ineff=
       F       F
Bank Sta=76.2,90.7
XS Rating Curve= 0 ,0
Exp/Cntr(USF)=0,0
Exp/Cntr=0.3,0.1

Type RM Length L Ch R = 1 ,917     ,188.9,187.7,185.5
XS GIS Cut Line= 2
2380481.04041391   653668.2353742380603.49402188653739.372558283
#Sta/Elev= 30
       0 3006.43     8.3 3003.21    14.7 3000.37    22.1 2996.05    23.5 2995.01
    26.4 2992.47    31.4 2986.23    33.7 2983.59    35.2  2982.2      41 2976.05
    46.9 2970.56    49.8  2968.2      522967.267    54.5 2966.52    55.7 2966.47
    64.4 2966.63      682967.262    73.5 2968.69    91.5 2967.62    96.1  2969.3
    99.5  2971.2   108.3 2976.95     110 2977.84   114.6 2979.51   119.3  2982.4
     123 2985.14   128.5 2989.62   133.2 2992.73   137.8 2994.83   141.6 2996.82
#Mann= 3, -1 ,  0
       0     0.1       0      52   0.045       0      68     0.1       0
Bank Sta=52,68
XS Rating Curve= 0 ,0
Exp/Cntr(USF)=0,0
Exp/Cntr=0.3,0.1

Type RM Length L Ch R = 1 ,729     ,107.6,110.6,112.8
XS GIS Cut Line= 3
  2380383.184252653840.5734260482380404.54145956653850.397741526
2380500.64889358653867.056363422
#Sta/Elev= 30
       0 2978.33     1.1 2977.52      11 2969.04    16.3 2964.77    23.5 2958.49
    27.2 2955.53    31.3 2952.72    35.3 2950.88      36 2950.76    39.4 2950.45
    42.9 2950.69    47.5 2951.36    51.6 2950.67    52.32950.427    55.6 2949.35
    59.7 2949.58    63.2 2950.41    63.7  2950.5    67.8 2952.34    71.9 2954.02
    75.9 2955.97      81 2959.63      84 2962.01    92.2 2967.29   100.3 2971.53
   104.3 2973.46   108.4 2975.17   112.4 2977.36   120.6 2981.41     121 2981.69
#Mann= 3, -1 ,  0
       0     0.1       0    52.3   0.045       0    63.2     0.1       0
Bank Sta=52.3,63.2
XS Rating Curve= 0 ,0
Exp/Cntr(USF)=0,0
Exp/Cntr=0.3,0.1

Type RM Length L Ch R = 1 ,619     ,165.9,165.4,164.9
XS GIS Cut Line= 2
2380335.77059436653916.1802983792380437.02889242653990.369061233
#Sta/Elev= 30
       0 2972.03     3.9 2969.47    12.5 2963.29    15.4 2961.06    20.3 2957.67
    25.3 2955.03    26.8  2954.1    30.3 2951.34    35.5 2947.68    40.2 2944.99
    42.3 2943.92    43.9 2943.24    49.1 2941.63    52.5 2940.09      55 2939.11
    55.8 2938.98    58.2 2939.03    65.32940.103    69.4 2941.14    72.6 2942.11
    75.4 2943.19    78.3 2944.93    81.1 2946.93    86.9 2950.62    92.6  2954.7
    96.4 2957.26   104.6 2961.27   114.6 2967.27   119.5 2969.88   125.5 2972.85
#Mann= 3, -1 ,  0
       0     0.1       0    52.5   0.045       0    65.3     0.1       0
Bank Sta=52.5,65.3
XS Rating Curve= 0 ,0
Exp/Cntr(USF)=0,0
Exp/Cntr=0.3,0.1

Type RM Length L Ch R = 1 ,454     ,152.7,153.2,151.8
XS GIS Cut Line= 2
2380229.03230311 654047.95667242  2380374.963285654131.413618274
#Sta/Elev= 30
       0  2967.2     8.2 2963.23    12.8 2960.67    29.6 2950.28    45.1 2940.02
    49.7 2936.31    54.3 2931.98    58.9 2928.43    63.5 2927.68    68.1 2928.77
    72.7  2927.8    77.3 2926.17      83 2925.79    88.2 2926.19    91.2 2926.95
    94.1 2928.22     105 2934.24   111.7 2935.88   114.6 2936.85   118.8  2939.7
   123.3 2944.02     128 2948.14   132.6 2951.02   139.4 2953.77   141.9 2955.18
   143.9 2956.73   149.8 2960.74   155.7 2963.93   160.3 2967.07   168.1 2973.08
#Mann= 3, -1 ,  0
       0     0.1       0    77.3   0.045       0    88.2     0.1       0
Bank Sta=77.3,88.2
XS Rating Curve= 0 ,0
Exp/Cntr(USF)=0,0
Exp/Cntr=0.3,0.1

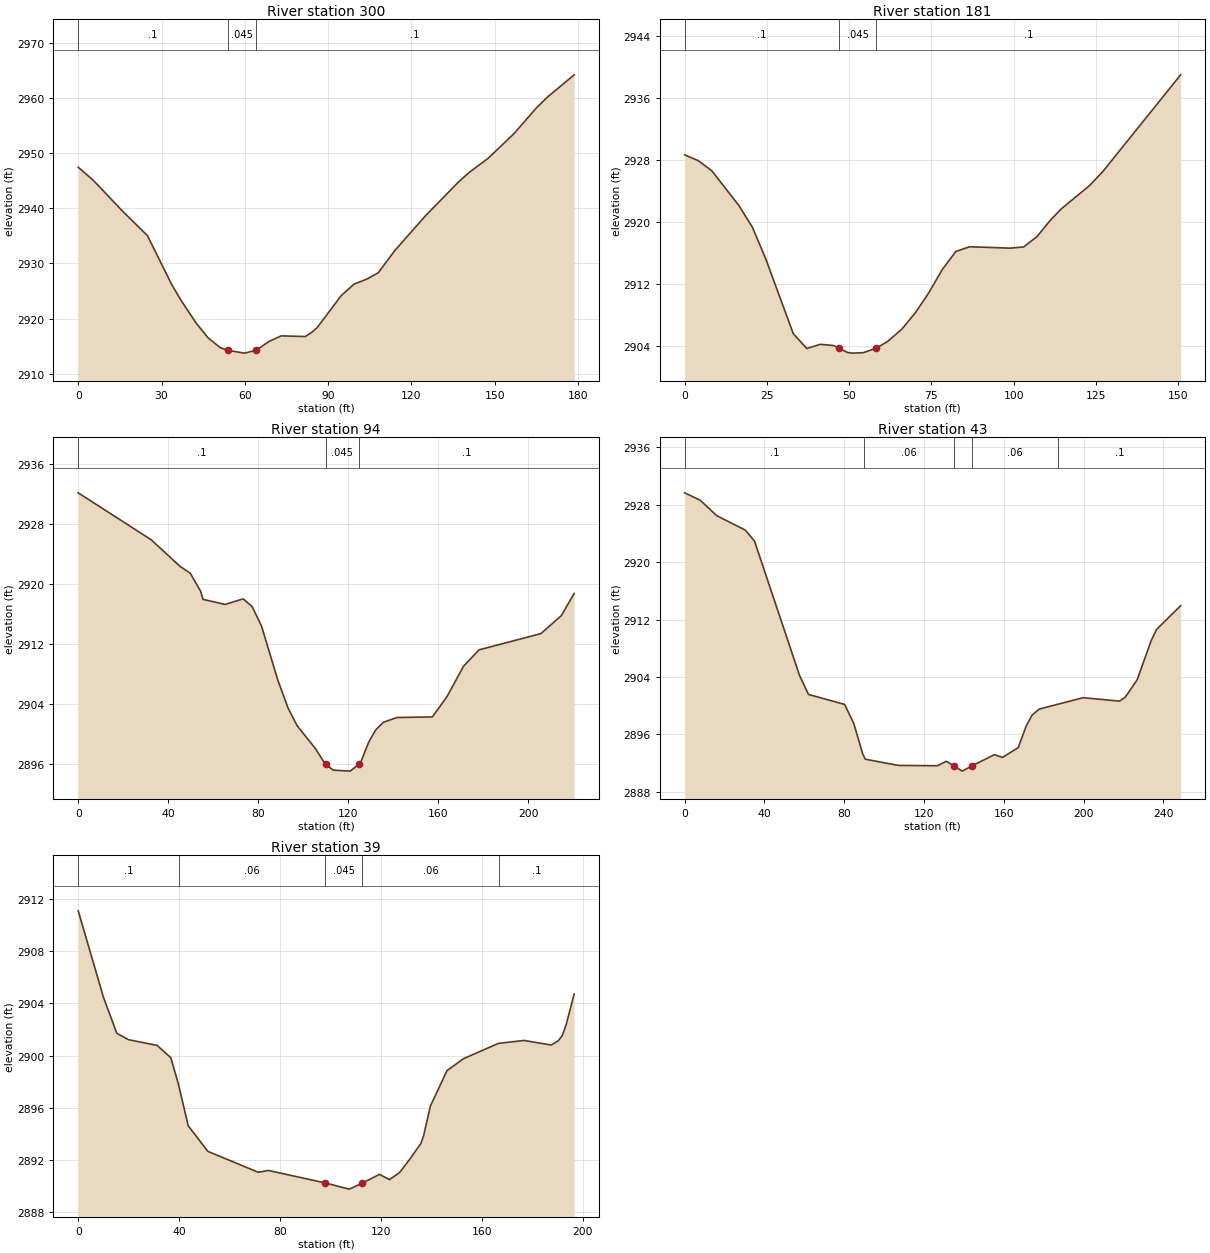
Type RM Length L Ch R = 1 ,300     ,119.7,119.2,117.7
XS GIS Cut Line= 3
2380157.39215189654182.9714598322380266.57019693654231.409606576
2380325.77237629654231.794036312
#Sta/Elev= 30
       0 2947.44     5.4 2945.09    15.9 2939.52    24.9 2935.07    33.7 2926.15
    37.1 2923.26    42.4 2919.24    46.8 2916.49    51.2 2914.73   53.86 2914.24
    59.9 2913.74    64.1 2914.26    68.7 2915.86    73.1 2916.87    81.8 2916.75
    84.4 2917.62    86.2 2918.46    94.7 2924.16    99.3 2926.24   104.1  2927.2
   108.1 2928.33   113.9 2932.27     125 2938.61     137  2944.8     141 2946.59
   147.5 2949.01     157 2953.57     165  2958.2     169 2960.17   178.6  2964.2
#Mann= 3, -1 ,  0
       0     0.1       0   53.86   0.045       0    64.1     0.1       0
Bank Sta=53.86,64.1
XS Rating Curve= 0 ,0
Exp/Cntr(USF)=0,0
Exp/Cntr=0.3,0.1

Type RM Length L Ch R = 1 ,181     ,88.2,87.4,86.5
XS GIS Cut Line= 3
2380120.21020403654303.2177097222380217.17192634 654327.56492634
2380267.57493619654321.584908223
#Sta/Elev= 30
       0 2928.69     4.1 2927.94     8.2 2926.65    16.5 2922.12    20.6 2919.31
    24.7 2915.17      33 2905.56    37.1 2903.64    41.2 2904.18    45.3 2904.02
    46.8  2903.7    49.5 2903.12      51 2903.04    54.3  2903.1   58.27 2903.69
    61.8 2904.59      66 2906.15    70.1 2908.26    74.2 2910.86    78.3 2913.87
    82.4 2916.19    86.6  2916.8    98.9 2916.62     103 2916.78     107 2918.09
   111.1 2920.22   114.4 2921.69   123.1 2924.74   127.2  2926.6   150.7 2939.04
#Mann= 3, -1 ,  0
       0     0.1       0    46.8   0.045       0   58.27     0.1       0
Bank Sta=46.8,58.27
XS Rating Curve= 0 ,0
Exp/Cntr(USF)=0,0
Exp/Cntr=0.3,0.1

Type RM Length L Ch R = 1 ,94      ,51.2,50.3,50.3
XS GIS Cut Line= 6
2380060.42447057654353.1348073032380086.40880748654402.200559356
2380140.25986174654398.9855710412380162.76477994654402.200559356
2380186.07344522654411.8455242992380241.13176673654381.380647534
#Sta/Elev= 30
       0 2932.16    32.4  2925.9    45.3 2922.33    49.8 2921.42    54.4 2919.02
    55.5 2917.93    65.3 2917.26    73.3    2918    77.3 2916.97    81.5 2914.34
    88.8 2907.07    93.3  2903.4    97.3 2901.06   105.4 2898.02   109.9  2895.9
   113.4 2895.13   120.9    2895   124.6  2895.9   125.6 2896.21     129 2898.81
   132.2  2900.5   135.6 2901.52   141.7 2902.16   157.4 2902.24   163.9 2904.95
   171.2 2908.99   178.1 2911.19   205.6 2913.36   214.7 2915.76   220.4 2918.72
#Mann= 3, -1 ,  0
       0     0.1       0   109.9   0.045       0   124.6     0.1       0
Bank Sta=109.9,124.6
XS Rating Curve= 0 ,0
Exp/Cntr(USF)=0,0
Exp/Cntr=0.3,0.1

Type RM Length L Ch R = 1 ,43      ,4,4.8,6.6
XS GIS Cut Line= 6
 2380041.2972853 654370.265981472380083.67620494654450.355328553
 2380119.0410764654448.7478343962380137.52725921654447.140340238
2380160.03217741654450.3553285532380230.60034115654409.847356353
#Sta/Elev= 30
       0 2929.67     7.8 2928.64    16.1 2926.48    30.4 2924.47      35 2922.96
    57.6 2904.21    62.1 2901.56    80.2 2900.17    84.8 2897.52    89.3 2893.26
    90.6 2892.53   107.1 2891.67   126.7 2891.62   131.2 2892.24     135 2891.61
   139.2 2890.87   144.12891.611   155.3 2893.16   159.4 2892.78   167.3 2894.16
   171.2 2897.12   174.1 2898.64   177.7 2899.51   199.8 2901.11   218.1 2900.63
     221  2901.2   226.9  2903.6   233.9 2909.04   236.6 2910.61   248.7 2913.94
#Mann= 5, -1 ,  0
       0     0.1       0      90    0.06       0     135   0.045       0
   144.1    0.06       0   187.3     0.1       0
Bank Sta=135,144.1
XS Rating Curve= 0 ,0
Exp/Cntr(USF)=0,0
Exp/Cntr=0.3,0.1

Type RM Length L Ch R = 1 ,39      ,,,
XS GIS Cut Line= 4
2380043.54950586654417.6941840742380072.44664283  654450.4050672
 2380165.6928068654452.8469965472380220.56158394654429.323201173
#Sta/Elev= 30
       0 2911.08      10 2904.47    15.3 2901.71    19.9 2901.22    31.3 2900.78
    36.7 2899.84    39.8 2897.76    43.6 2894.63    51.4 2892.67    71.4 2891.07
    75.4 2891.21      98 2890.25   107.4 2889.78   112.52890.223   119.4 2890.91
   123.4 2890.51   127.4 2891.05   131.4 2892.06   135.8 2893.26   136.9 2893.85
   139.6 2896.13   146.2 2898.85   152.7 2899.76   166.5 2900.93   176.7 2901.16
   187.5 2900.81   190.3 2901.13   191.9 2901.54   193.4 2902.35   196.6 2904.71
#Mann= 5, -1 ,  0
       0     0.1       0      40    0.06       0      98   0.045       0
   112.5    0.06       0  166.92     0.1       0
Bank Sta=98,112.5
XS Rating Curve= 0 ,0
Exp/Cntr(USF)=0,0
Exp/Cntr=0.3,0.1
LCMann Table=0

Chan Stop Cuts=-1
Use User Specified Reach Order=0
Composite Channel Slope=5